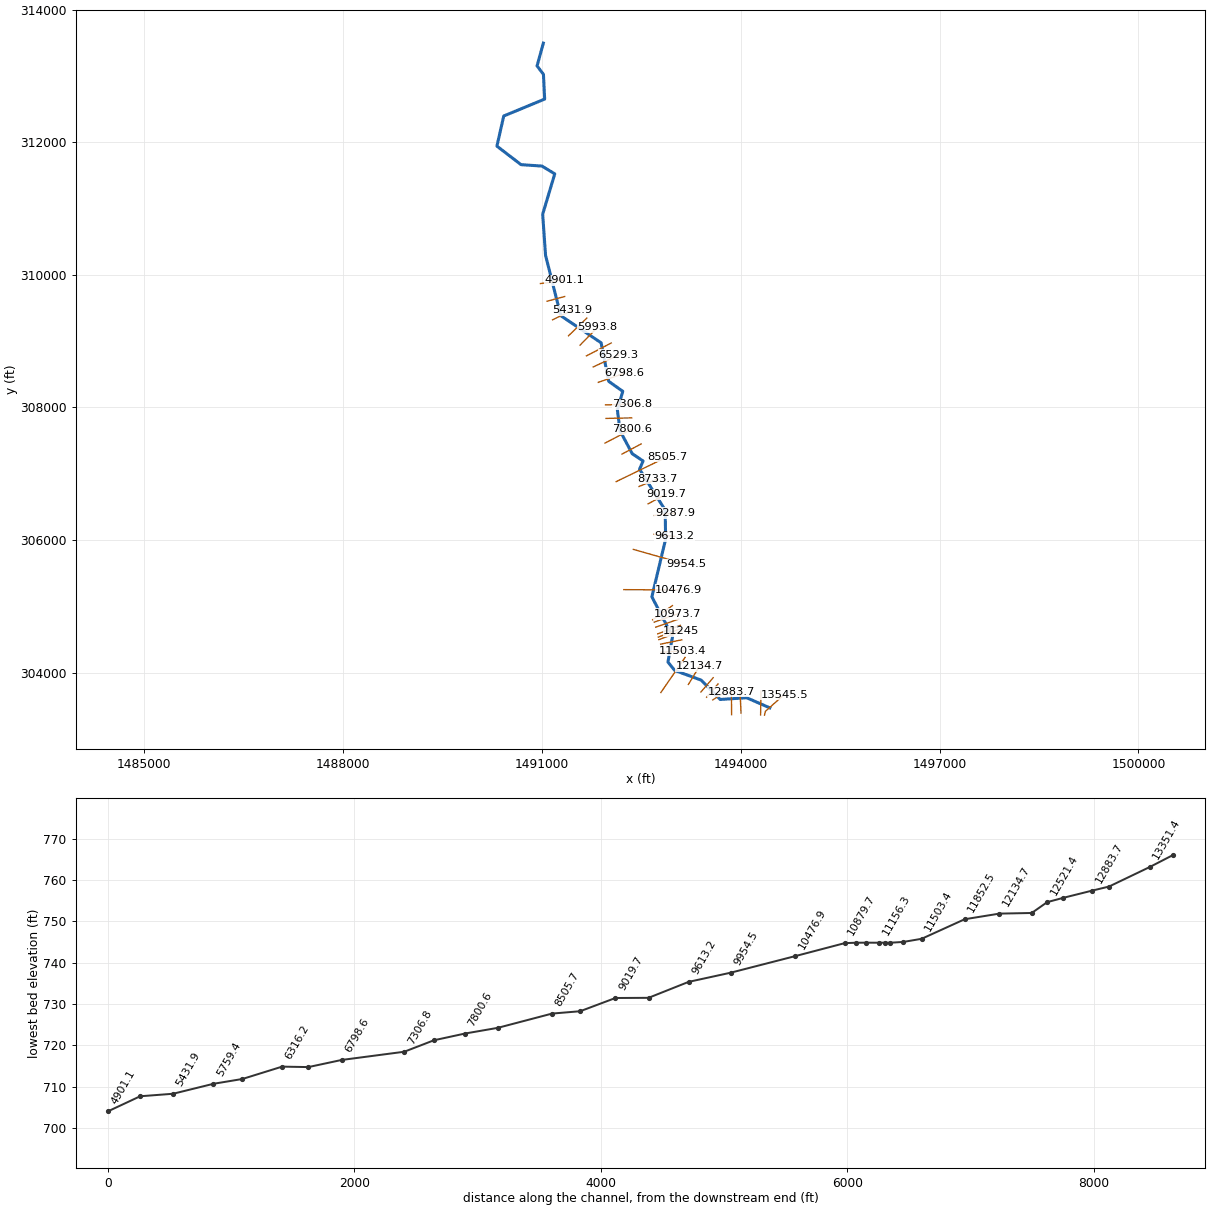
--- RFkFrencCr.prj (project) ---

Proj Title=RFkFrencCr
Current Plan=p01
Default Exp/Contr=0,0
English Units
Geom File=g01
Flow File=f01
Plan File=p01
BEGIN DESCRIPTION:
AMEC Environment & Infrastructure, 2013
Projection: NAD 1983 State Plane West Virginia North FIPS 4701 (US Feet)
Vertical Datum: NAVD 1988
END DESCRIPTION:
DSS Export Rating Curves= 0
DSS Export Rating Curve Sorted= 0
DSS Export Volume Flow Curves= 0
DXF OffsetX= 0
DXF OffsetY= 0
DXF ScaleX= 0
DXF ScaleY= 0

--- RFkFrencCr.p01 (plan) ---

Plan Title=Floodplain
Program Version=4.00
Geom File=g01
Flow File=f01
K Sum by GR=0
Std Step Tol=0.01
Critical Tol=0.01
Num of Std Step Trials=20
Max Error Tol=0.3
Flow Tol Ratio=0.001
Split Flow NTrial=30
Split Flow Tol=0.02
Split Flow Ratio=0.02
Log Output Level=0
Friction Slope Method=1
Unsteady Friction Slope Method=2
Unsteady Bridges Friction Slope Method=1
Global Log Level=0
CheckData=False
Run HTab=0
Run UNet=0
Run PostProcess=0
UNET Theta=0
UNET Theta Warmup=0
UNET ZTol=0
UNET ZSATol=0
UNET MxIter=0
UNET MaxInSteps=0
UNET DtIC=0
UNET DtMin=0
UNET MaxCRTS=0
UNET WFStab=0
UNET SFStab=0
UNET WFX=0
UNET SFX=0
UNET DSS MLevel=0
UNET DZMax Abort=0
UNET Convert EG Bridges=0
UNET Use Existing IB Tables=0
UNET Froude Limit=0
UNET Froude Power=0
Write IC File=0
Echo Input=False
Echo Output=False
Write Detailed=0

--- RFkFrencCr.f01 (steady flow) ---

Flow Title=USGS Regress. Eqn. (2010) - Western-Plateaus
Program Version=4.00
Number of Profiles=1
Profile Names=P100yr
River Rch & RM=RFkFrencCr,Main      ,13545.5
     822
River Rch & RM=RFkFrencCr,Main      ,13351.4
     823
River Rch & RM=RFkFrencCr,Main      ,13022.7
     985
River Rch & RM=RFkFrencCr,Main      ,11852.5
    1085
River Rch & RM=RFkFrencCr,Main      ,11503.4
    1236
River Rch & RM=RFkFrencCr,Main      ,9613.2
    1335
River Rch & RM=RFkFrencCr,Main      ,7306.8
    1469
River Rch & RM=RFkFrencCr,Main      ,594.3
    1623
River Rch & RM=RFkFrencCr,Main      ,249.5
    1624
Boundary for River Rch & Prof#=RFkFrencCr,Main      ,1
Up Type=0
Dn Type=3
Dn Slope=0.004822

--- RFkFrencCr.g01 (geometry) ---

Geom Title=USGS 3m DEM
Program Version=4.10

River Reach=RFkFrencCr      ,Main
Reach XY= 30
       1494438.8      303469.321     1494091.039      303621.511
     1493691.299       303595.47     1493404.841      303887.136
     1493006.403       304032.97     1492903.539      304159.272
     1492972.549      304543.386     1492661.351      305143.647
     1492868.382      306013.438     1492861.872      306450.938
     1492475.153      307068.126     1492528.539      307191.824
     1492364.476      307302.501     1492180.882      307647.553
     1492140.518      307963.959     1492222.549      308242.605
     1492009.945      308393.217     1491895.726      308974.376
     1491287.653       309383.23      1491057.59      310294.351
     1491014.269       310913.49     1491196.507      311522.553
     1491003.799       311639.74     1490688.364       311661.27
     1490324.111      311940.522     1490426.976      312394.949
     1491044.164      312650.157     1491025.934      313023.855
      1490929.58      313150.157     1491024.398      313493.502

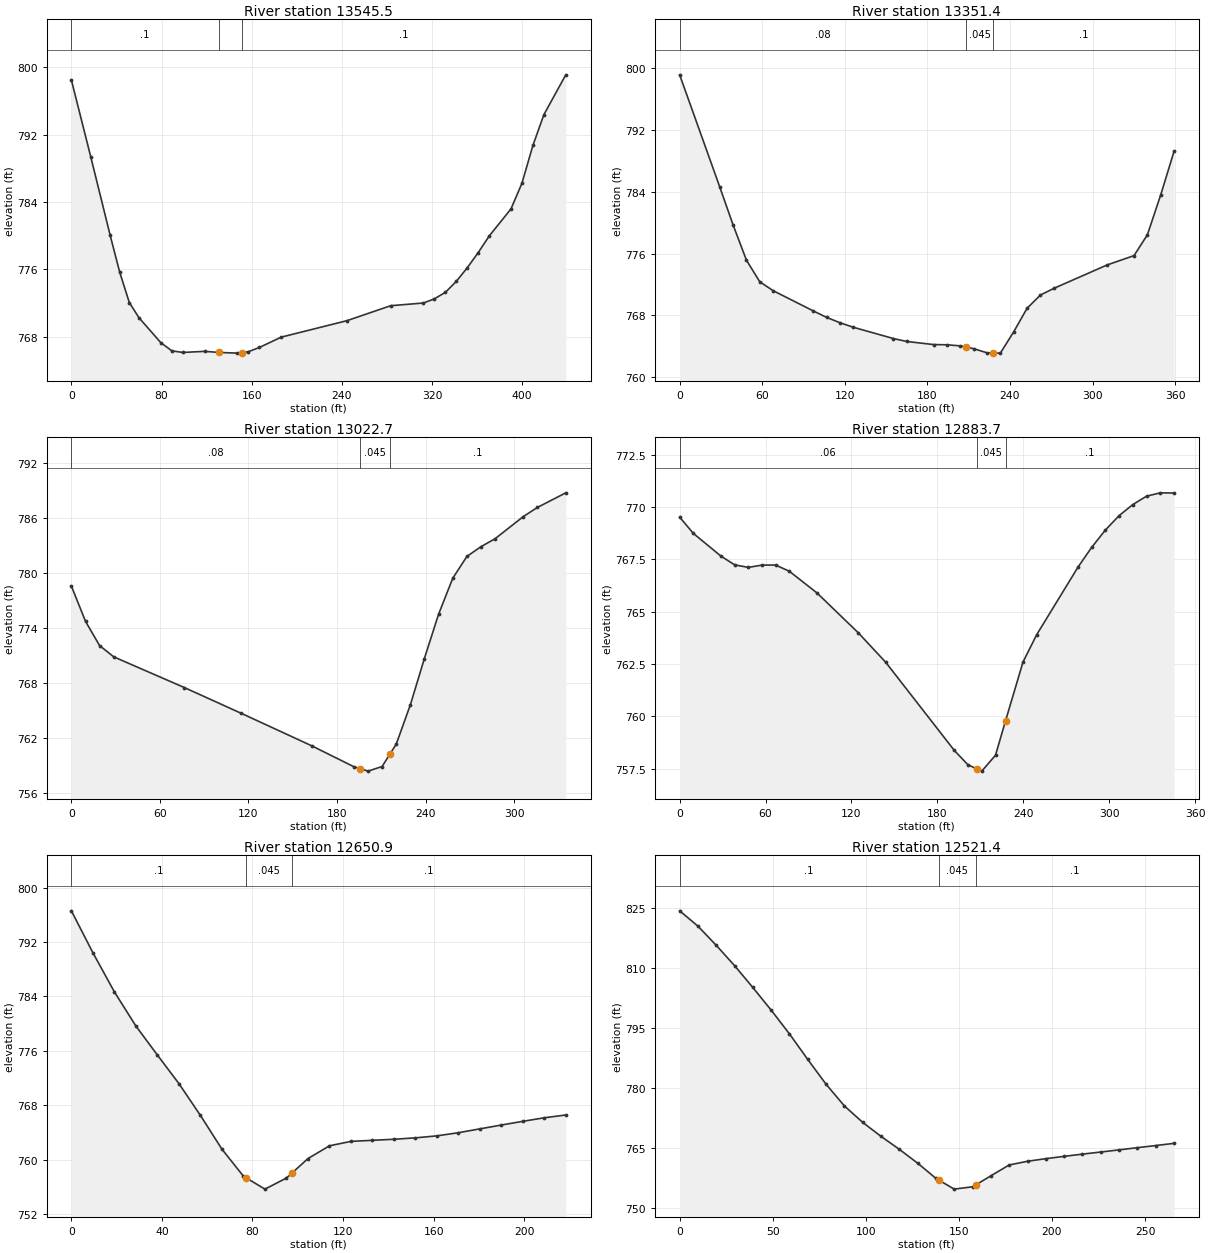
Type RM Length L Ch R = 1 ,13545.5 ,181,194.1,201.4
XS GIS Cut Line= 3
     1494359.476      303358.479     1494373.102      303416.937
     1494656.351      303668.375
#Sta/Elev= 30
       0  798.49    17.2  789.37    34.3  780.12    42.9  775.67    51.4  772.08
      60  770.27    79.4  767.31    89.2  766.34    98.9  766.15   118.3  766.28
   131.1  766.15   147.4  766.07   151.1  766.13   157.1  766.24   166.8  766.74
   186.3  767.97   244.5  769.92   283.4   771.7   312.5  772.02   322.2  772.52
     332  773.29   341.7   774.6   351.4  776.21   361.1  778.01   370.8  779.97
   390.2   783.2   399.9  786.24   409.6  790.72   419.4  794.39   438.8  799.11
#Mann= 3 , 0 , 0
       0      .1       0   131.1    .045       0   151.1      .1       0
Bank Sta=131.1,151.1
XS Rating Curve= 0 ,0
Exp/Cntr=0.3,0.1

Type RM Length L Ch R = 1 ,13351.4 ,327.3,328.7,330.2
XS GIS Cut Line= 2
     1494301.053      303361.801     1494305.986      303720.986
#Sta/Elev= 29
       0  799.17    29.1  784.65    38.8  779.72    48.5  775.15    58.2  772.34
      68  771.18    97.1  768.56   106.8  767.72   116.5  767.03   126.2  766.44
   155.3  764.98     165   764.6   184.5   764.2   194.2  764.17   203.9  764.03
   207.9  763.88   213.6  763.67   223.3  763.13   227.9  763.11     233  763.09
   242.7  765.85   252.4   768.9   262.1  770.62   271.8  771.48   310.7  774.53
   330.1  775.73   339.8  778.42   349.5   783.6   359.2  789.25
#Mann= 3 , 0 , 0
       0     .08       0   207.9    .045       0   227.9      .1       0
Bank Sta=207.9,227.9
XS Rating Curve= 0 ,0
Exp/Cntr=0.3,0.1

Type RM Length L Ch R = 1 ,13022.7 ,138.4,139.1,137.3
XS GIS Cut Line= 2
     1494005.765      303390.312     1493989.623      303724.878
#Sta/Elev= 23
       0  778.55     9.6   774.7    19.1  772.07    28.7  770.84    76.6  767.49
   114.8  764.71   162.7  761.16   191.4  758.87   195.7  758.66     201  758.39
   210.5  758.89   215.7  760.21   220.1  761.32   229.7  765.62   239.2  770.66
   248.8  775.48   258.4   779.4     268  781.78   277.5  782.84   287.1  783.71
   306.2  786.12   315.8  787.12     335  788.71
#Mann= 3 , 0 , 0
       0     .08       0   195.7    .045       0   215.7      .1       0
Bank Sta=195.7,215.7
XS Rating Curve= 0 ,0
Exp/Cntr=0.3,0.1

Type RM Length L Ch R = 1 ,12883.7 ,247.9,232.7,216.6
XS GIS Cut Line= 2
     1493863.457      303366.421     1493860.905      303711.698
#Sta/Elev= 27
       0  769.52     9.6  768.74    28.8  767.66    38.4  767.24      48  767.12
    57.6  767.23    67.1  767.23    76.7  766.93    95.9   765.9   124.7     764
   143.9  762.59   191.8  758.38   201.4  757.69   207.6   757.5     211  757.39
   220.6  758.15   227.6  759.79   239.8   762.6   249.4  763.91   278.2  767.13
   287.7  768.07   297.3   768.9   306.9  769.59   316.5  770.12   326.1  770.52
   335.7  770.68   345.3  770.67
#Mann= 3 , 0 , 0
       0     .06       0   207.6    .045       0   227.6      .1       0
Bank Sta=207.6,227.6
XS Rating Curve= 0 ,0
Exp/Cntr=0.3,0.1

Type RM Length L Ch R = 1 ,12650.9 ,125.1,129.6,133.9
XS GIS Cut Line= 2
     1493579.392       303588.74     1493763.786       303705.83
#Sta/Elev= 26
       0  796.58     9.5  790.42      19  784.66    28.5  779.64      38  775.37
    47.5  771.18      57   766.5    66.5  761.54      76  757.56    77.3   757.3
    85.5  755.66      95  757.29    97.3  757.98   104.5  760.15     114  762.03
   123.5  762.68     133  762.84   142.4  762.99     152   763.2   161.4  763.49
   170.9  763.95   180.4  764.52   189.9  765.08   199.4  765.63   208.9  766.15
   218.4  766.56
#Mann= 3 , 0 , 0
       0      .1       0    77.3    .045       0    97.3      .1       0
Bank Sta=77.3,97.3
XS Rating Curve= 0 ,0
Exp/Cntr=0.3,0.1

Type RM Length L Ch R = 1 ,12521.4 ,126.1,125.3,122.3
XS GIS Cut Line= 2
     1493486.642      303628.937     1493659.489      303830.554
#Sta/Elev= 30
       0  824.23     9.8  820.41    19.7  815.58    29.5  810.52    39.3  805.06
    49.2  799.37      59  793.44    68.8  787.07    78.7  780.83    88.5  775.43
    98.4  771.29   108.2  767.81     118  764.58   127.9   761.1   137.7   757.3
   139.2  756.89   147.5  754.62   157.4  755.21   159.2  755.71   167.2  757.95
     177  760.66   186.9  761.59   196.7  762.24   206.6  762.82   216.4  763.38
   226.2   763.9   236.1  764.44   245.9  764.99   255.7  765.52   265.6  766.07
#Mann= 3 , 0 , 0
       0      .1       0   139.2    .045       0   159.2      .1       0
Bank Sta=139.2,159.2
XS Rating Curve= 0 ,0
Exp/Cntr=0.3,0.1

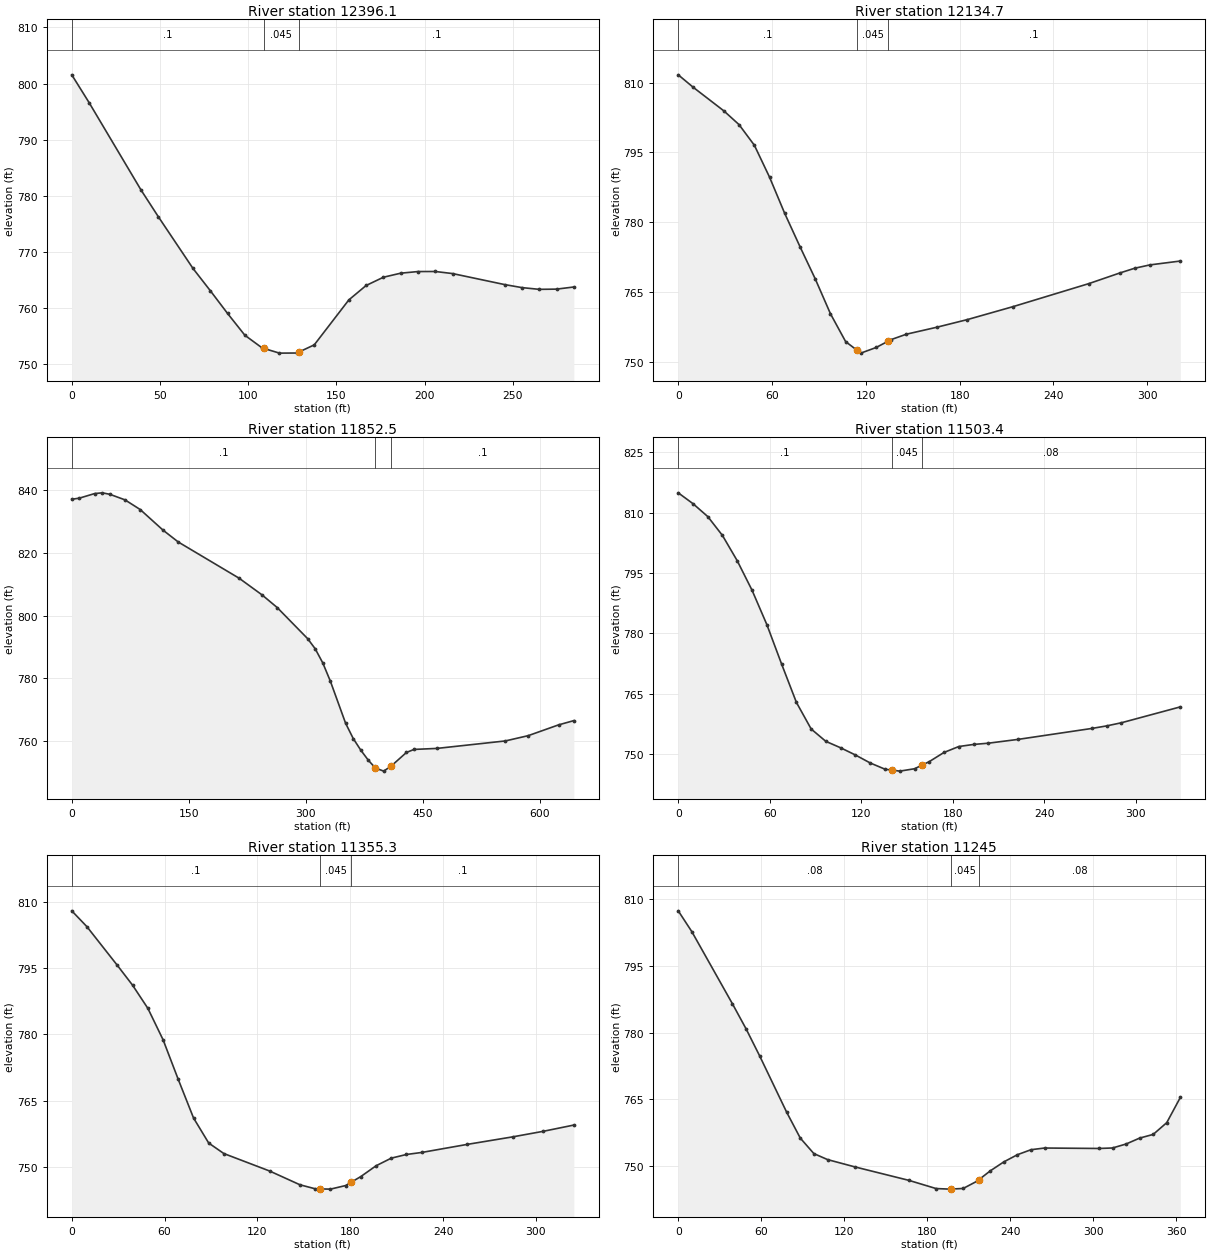
Type RM Length L Ch R = 1 ,12396.1 ,258,261.4,266.4
XS GIS Cut Line= 2
     1493400.405      303707.297     1493585.579      303923.293
#Sta/Elev= 26
       0  801.57     9.8  796.63    39.2  781.08      49  776.32    68.7  767.08
    78.5  763.12    88.3  759.06    98.1  755.18   107.9  752.92   108.8  752.84
   117.7     752   127.5  752.02   128.8  752.21   137.4  753.47     157  761.48
   166.8  764.05   176.6  765.52   186.4  766.24   196.2  766.53     206  766.54
   215.8  766.17   245.3  764.21   255.1  763.67   264.9  763.36   274.7   763.4
   284.5  763.78
#Mann= 3 , 0 , 0
       0      .1       0   108.8    .045       0   128.8      .1       0
Bank Sta=108.8,128.8
XS Rating Curve= 0 ,0
Exp/Cntr=0.3,0.1

Type RM Length L Ch R = 1 ,12134.7 ,282.9,282.2,281.3
XS GIS Cut Line= 2
     1493211.591      303822.182     1493379.095        304096.3
#Sta/Elev= 25
       0  811.65     9.7  808.94    29.2   803.9    38.9  800.95    48.7  796.52
    58.4  789.67    68.1  781.89    77.9  774.72    87.6  767.84    97.4   760.3
   107.1  754.32   114.3  752.49   116.8  751.85   126.6  753.06   134.3  754.42
   136.3  754.77     146  755.92   165.5  757.42     185  759.06   214.2  761.84
   262.8   766.8   282.3  769.05     292  770.09   301.8  770.81   321.2  771.64
#Mann= 3 , 0 , 0
       0      .1       0   114.3    .045       0   134.3      .1       0
Bank Sta=114.3,134.3
XS Rating Curve= 0 ,0
Exp/Cntr=0.3,0.1

Type RM Length L Ch R = 1 ,11852.5 ,362.7,349.1,335.4
XS GIS Cut Line= 2
     1492796.516      303699.607     1493161.455      304229.468
#Sta/Elev= 30
       0  837.04     9.8   837.4    29.2  838.85      39  839.09    48.7  838.63
    68.2  836.85    87.7  833.77     117   827.2   136.5  823.43   214.5   811.9
   243.7  806.62   263.2  802.58   302.2  792.68   311.9  789.46   321.7  784.92
   331.4  779.12   350.9  765.74   360.7  760.86   370.4  757.16   380.2   753.9
   389.2  751.47   399.7  750.49   409.2  752.08   428.9  756.44   438.7   757.4
   467.9  757.72   555.6   760.1   584.9  761.78   623.9  765.22   643.4  766.57
#Mann= 3 , 0 , 0
       0      .1       0   389.2    .045       0   409.2      .1       0
Bank Sta=389.2,409.2
XS Rating Curve= 0 ,0
Exp/Cntr=0.3,0.1

Type RM Length L Ch R = 1 ,11503.4 ,146,148.1,149.9
XS GIS Cut Line= 2
     1492800.702      304306.063     1493129.192      304328.974
#Sta/Elev= 29
       0   814.9     9.7   812.2    19.4  808.99      29  804.31    38.7  798.02
    48.4  790.71    58.1  782.18    67.8  772.36    77.5  762.84    87.2  756.22
    96.8  753.16   106.5  751.56   116.2  749.77   125.9  747.79   135.6  746.24
     140  746.02   145.3  745.76     155  746.35     160  747.27   164.6  748.11
   174.3   750.4     184  751.87   193.7  752.39   203.4   752.7   222.8  753.64
   271.2  756.36   280.9  756.99   290.6  757.77   329.3  761.72
#Mann= 3 , 0 , 0
       0      .1       0     140    .045       0     160     .08       0
Bank Sta=140,160
XS Rating Curve= 0 ,0
Exp/Cntr=0.3,0.1

Type RM Length L Ch R = 1 ,11355.3 ,107.7,110.3,113.5
XS GIS Cut Line= 2
     1492793.567      304430.062     1493111.504      304495.011
#Sta/Elev= 26
       0  807.98     9.8  804.39    29.5  795.62    39.3  791.15    49.2   785.9
      59  778.81    68.8  769.85    78.7   761.1    88.5  755.43    98.3  753.05
   127.8  749.11   147.5  745.98   157.3  745.08   160.5  745.05   167.2     745
     177  745.81   180.5  746.54   186.8  747.84   196.7  750.29   206.5  752.01
   216.3  752.84   226.2   753.3   255.7  755.13   285.2  756.84   304.8  758.09
   324.5   759.5
#Mann= 3 , 0 , 0
       0      .1       0   160.5    .045       0   180.5      .1       0
Bank Sta=160.5,180.5
XS Rating Curve= 0 ,0
Exp/Cntr=0.3,0.1

Type RM Length L Ch R = 1 ,11245   ,39.3,39.3,39.3
XS GIS Cut Line= 2
     1492766.983      304497.429     1493106.436      304625.453
#Sta/Elev= 29
       0  807.36     9.8  802.69    39.2  786.44      49  780.84    58.8  774.77
    78.4  762.06    88.2  756.27      98  752.79   107.9  751.44   127.5  749.81
   166.7  746.77   186.3  744.93   196.1   744.8     197  744.81   205.9  744.95
   215.7  746.55     217  746.86   225.5  748.91   235.3  750.93   245.1  752.54
   254.9  753.66   264.7  754.04     304  753.94   313.8  754.05   323.6  754.94
   333.4  756.27   343.2   757.1     353  759.74   362.8   765.4
#Mann= 3 , 0 , 0
       0     .08       0     197    .045       0     217     .08       0
Bank Sta=197,217
XS Rating Curve= 0 ,0
Exp/Cntr=0.3,0.1

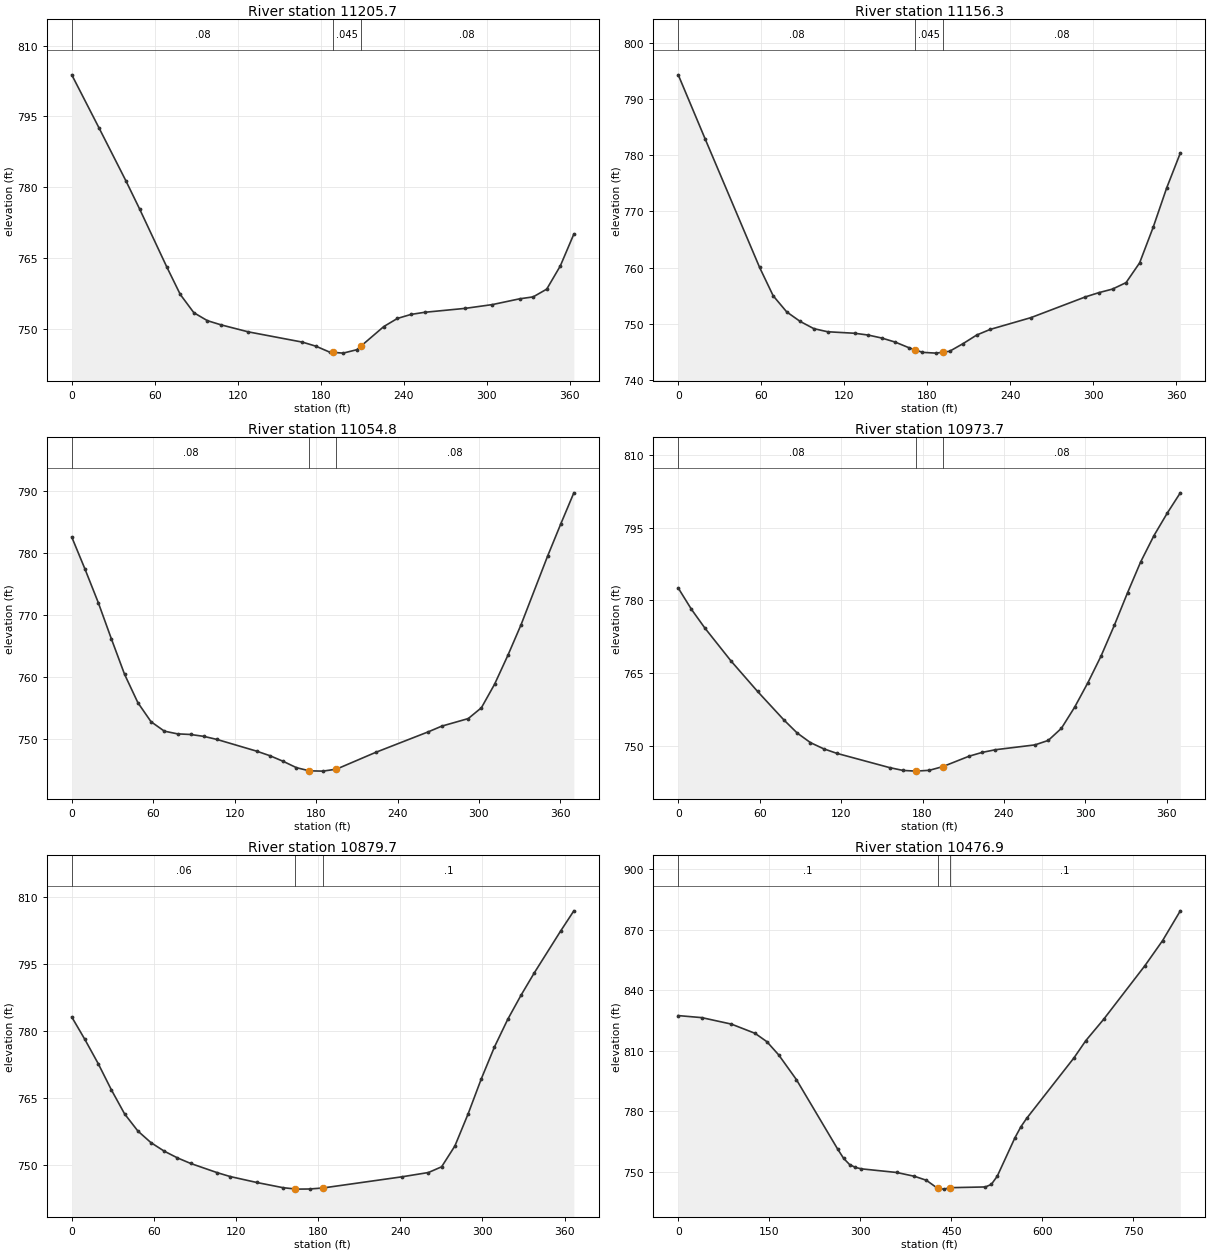
Type RM Length L Ch R = 1 ,11205.7 ,49.2,49.4,49.2
XS GIS Cut Line= 2
     1492757.732      304535.746     1493097.185       304663.77
#Sta/Elev= 28
       0   803.8    19.6   792.6    39.2  781.29      49  775.38    68.6  763.12
    78.4  757.26    88.2  753.39      98   751.7   107.9  750.81   127.5  749.33
   166.7  747.15   176.5  746.28   186.3  745.04   188.7  744.99   196.1  744.82
   205.9  745.54   208.7  746.24   225.5  750.46   235.3  752.17   245.1  753.02
   254.9  753.47   284.4  754.31     304  755.11   323.6  756.33   333.4  756.74
   343.2  758.38     353  763.29   362.8  770.05
#Mann= 3 , 0 , 0
       0     .08       0   188.7    .045       0   208.7     .08       0
Bank Sta=188.7,208.7
XS Rating Curve= 0 ,0
Exp/Cntr=0.3,0.1

Type RM Length L Ch R = 1 ,11156.3 ,101.7,101.5,101.1
XS GIS Cut Line= 2
     1492751.184      304585.683     1493090.637      304713.707
#Sta/Elev= 30
       0  794.26    19.6  782.78    58.8  760.04    68.6     755    78.4  752.13
    88.2  750.43      98  749.16   107.9  748.61   127.5  748.34   137.3  748.02
   147.1  747.49   156.9  746.76   166.7  745.77   171.4  745.38   176.5  744.95
   186.3  744.81   191.4  744.98   196.1  745.14   205.9  746.51   215.7  748.03
   225.5  749.03   254.9  751.12   294.2   754.8     304  755.56   313.8  756.19
   323.6  757.34   333.4  760.85   343.2  767.18     353   774.2   362.8  780.36
#Mann= 3 , 0 , 0
       0     .08       0   171.4    .045       0   191.4     .08       0
Bank Sta=171.4,191.4
XS Rating Curve= 0 ,0
Exp/Cntr=0.3,0.1

Type RM Length L Ch R = 1 ,11054.8 ,81.3,81.2,81.2
XS GIS Cut Line= 2
     1492719.904      304685.711       1493068.8      304808.702
#Sta/Elev= 30
       0  782.63     9.7  777.48    19.5  772.06    29.2  766.18    38.9  760.46
    48.7  755.88    58.4   752.8    68.2  751.28    77.9  750.84    87.6  750.74
    97.4  750.43   107.1  749.93   136.3  748.04     146  747.31   155.8   746.4
   165.5  745.38     175  744.87     185  744.82     195  745.14   223.9  747.85
   262.8  751.18   272.6  752.09   292.1  753.31   301.8  755.06   311.5  758.86
   321.3  763.53     331  768.47   350.5  779.52   360.2  784.72   369.9  789.78
#Mann= 3 , 0 , 0
       0     .08       0     175    .045       0     195     .08       0
Bank Sta=175,195
XS Rating Curve= 0 ,0
Exp/Cntr=0.3,0.1

Type RM Length L Ch R = 1 ,10973.7 ,89.6,94,98.4
XS GIS Cut Line= 2
      1492696.15      304761.922     1493045.046      304884.913
#Sta/Elev= 30
       0  782.57     9.7  778.19    19.5  774.36    38.9  767.52    58.4  761.26
    77.9  755.35    87.6  752.68    97.4  750.69   107.1  749.42   116.8  748.48
   155.8  745.53   165.5  744.96     175  744.81     185  744.98     195  745.75
   214.2  747.88   223.9  748.67   233.6  749.22   262.8  750.22   272.6  751.14
   282.3  753.64   292.1  758.02   301.8  763.04   311.5  768.54   321.3  774.89
     331  781.58   340.7  787.96   350.5  793.39   360.2  797.98   369.9   802.2
#Mann= 3 , 0 , 0
       0     .08       0     175    .045       0     195     .08       0
Bank Sta=175,195
XS Rating Curve= 0 ,0
Exp/Cntr=0.3,0.1

Type RM Length L Ch R = 1 ,10879.7 ,412.2,402.7,393.2
XS GIS Cut Line= 2
     1492673.362      304797.224     1492971.056      305011.451
#Sta/Elev= 30
       0  783.22     9.6  778.19    19.3   772.8      29  766.89    38.6  761.54
    48.3  757.71    57.9   755.1    67.6   753.2    77.2   751.7    86.9  750.45
   106.2   748.4   115.8  747.52   135.1   746.2   154.4  745.03   163.3  744.74
   164.1  744.71   173.7  744.74   183.3  744.96   241.3  747.47   260.6  748.43
   270.2  749.71   279.9  754.37   289.6  761.58   299.2   769.4   308.8  776.52
   318.5   782.7   328.2  788.09   337.8  793.05   357.1  802.44   366.8  806.98
#Mann= 3 , 0 , 0
       0     .06       0   163.3    .045       0   183.3      .1       0
Bank Sta=163.3,183.3
XS Rating Curve= 0 ,0
Exp/Cntr=0.3,0.1

Type RM Length L Ch R = 1 ,10476.9 ,526.8,522.4,518.2
XS GIS Cut Line= 2
     1492238.688      305252.049     1493065.987      305247.411
#Sta/Elev= 30
       0  827.41    38.9   826.4    87.6   823.2   126.5  818.65     146  814.52
   165.5  807.98   194.7  795.75   262.8  761.32   272.5  756.79   282.3  753.73
     292  752.29   301.7   751.6   360.1  749.79   389.3   747.9   408.8  745.95
   427.5  741.93     438  741.56   447.5  742.27   506.1  742.64   515.8  743.88
   525.6  747.92   554.8  766.97   564.5  772.36   574.2  776.61   652.1  806.51
   671.6  815.03   700.8  825.51   768.9  852.08   798.1  864.51   827.3  879.24
#Mann= 3 , 0 , 0
       0      .1       0   427.5    .045       0   447.5      .1       0
Bank Sta=427.5,447.5
XS Rating Curve= 0 ,0
Exp/Cntr=0.3,0.1

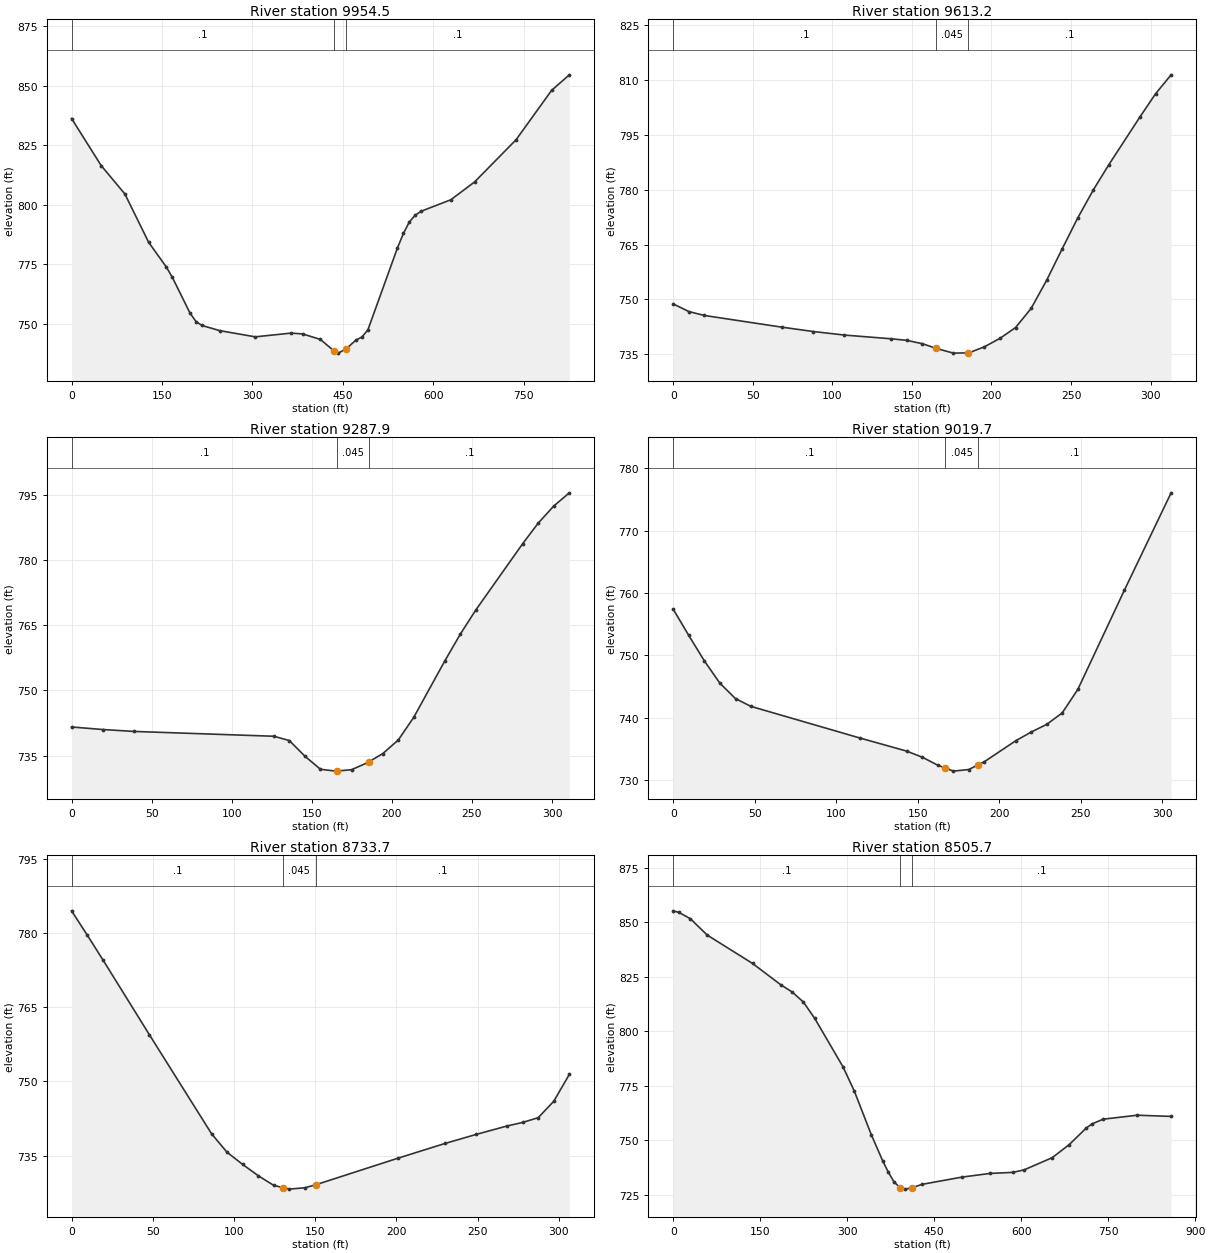
Type RM Length L Ch R = 1 ,9954.5  ,338.6,341.3,344
XS GIS Cut Line= 2
     1492381.771      305859.063     1493176.225      305633.533
#Sta/Elev= 30
       0  836.14    49.2  816.34    88.5  804.43   127.8  784.17   157.3  773.72
   167.1  769.45   196.6  754.35   206.5  750.82   216.3  749.19   245.8  747.01
   304.8   744.4   363.8  745.97   383.4  745.63   412.9   743.3   435.4  738.47
   442.4  737.56   455.4  739.33   471.9  743.06   481.7  744.32   491.6  747.34
   540.7   781.8   550.6  787.88   560.4   792.7   570.2  795.53   580.1  797.19
   629.2     802   668.5  809.46   737.4  827.21   796.4  847.97   825.8  854.49
#Mann= 3 , 0 , 0
       0      .1       0   435.4    .045       0   455.4      .1       0
Bank Sta=435.4,455.4
XS Rating Curve= 0 ,0
Exp/Cntr=0.3,0.1

Type RM Length L Ch R = 1 ,9613.2  ,322,325.3,328.7
XS GIS Cut Line= 2
     1492694.579      306086.465     1493005.938      306055.238
#Sta/Elev= 25
       0  748.77     9.8  746.69    19.6  745.62    68.4  742.42      88  741.24
   107.6  740.27   136.9  739.26   146.7  738.83   156.5  737.92   165.1  736.66
     176  735.34   185.1  735.41   185.8  735.42   195.6  737.08   205.4  739.39
   215.1  742.32   224.9  747.54   234.7  755.27   244.5  763.88   254.2  772.25
     264  779.91   273.8  786.83   293.4   799.9   303.1  806.16   312.9  811.35
#Mann= 3 , 0 , 0
       0      .1       0   165.1    .045       0   185.1      .1       0
Bank Sta=165.1,185.1
XS Rating Curve= 0 ,0
Exp/Cntr=0.3,0.1

Type RM Length L Ch R = 1 ,9287.9  ,262.6,268.2,273.6
XS GIS Cut Line= 2
     1492698.709      306369.891     1493007.219      306407.861
#Sta/Elev= 22
       0  741.62    19.4  741.04    38.8   740.6   126.3  739.49     136   738.5
   145.7  734.91   155.4   731.9   165.1  731.48   165.9  731.51   174.8   731.8
   184.6   733.4   185.9  733.68   194.3   735.5     204  738.63   213.7  743.87
   233.1  756.83   242.8  762.99   252.6   768.6   281.7  783.74   291.4  788.46
   301.1  792.38   310.8   795.4
#Mann= 3 , 0 , 0
       0      .1       0   165.9    .045       0   185.9      .1       0
Bank Sta=165.9,185.9
XS Rating Curve= 0 ,0
Exp/Cntr=0.3,0.1

Type RM Length L Ch R = 1 ,9019.7  ,287.6,286.1,284.5
XS GIS Cut Line= 2
     1492605.543      306546.486     1492874.552      306691.109
#Sta/Elev= 22
       0  757.38     9.5   753.2    19.1   749.1    28.6  745.54    38.2  743.06
    47.7  741.82   114.5  736.75   143.2  734.65   152.7  733.68   162.2   732.4
   166.9  731.93   171.8  731.44   181.3   731.7   186.9  732.44   190.9  732.96
     210   736.3   219.5   737.7   229.1  738.94   238.6  740.78   248.2  744.56
   276.8   760.5   305.4  776.08
#Mann= 3 , 0 , 0
       0      .1       0   166.9    .045       0   186.9      .1       0
Bank Sta=166.9,186.9
XS Rating Curve= 0 ,0
Exp/Cntr=0.3,0.1

Type RM Length L Ch R = 1 ,8733.7  ,227.1,228,229
XS GIS Cut Line= 2
     1492467.773      306807.631     1492751.574      306923.005
#Sta/Elev= 21
       0  784.47     9.6   779.6    19.2  774.62    47.9  759.44    86.2  739.42
    95.7  735.69   105.3  733.24   114.9  730.95   124.5  728.99   130.2  728.54
     134  728.24   143.6  728.51   150.2  729.11     201   734.5   229.8  737.46
   248.9  739.28   268.1     741   277.6  741.71   287.2  742.67   296.8  745.99
   306.4  751.43
#Mann= 3 , 0 , 0
       0      .1       0   130.2    .045       0   150.2      .1       0
Bank Sta=130.2,150.2
XS Rating Curve= 0 ,0
Exp/Cntr=0.3,0.1

Type RM Length L Ch R = 1 ,8505.7  ,439.3,440.2,441
XS GIS Cut Line= 2
     1492123.274      306881.214       1492895.6       307256.14
#Sta/Elev= 30
       0  855.19     9.8  854.43    29.3   851.6    58.5  844.08   136.6  831.09
   185.4   821.3   204.9  818.02   224.4  813.38   243.9   805.9   292.7   783.7
   312.2  772.58   341.5  752.58     361   740.7   370.7  735.49   380.5  731.03
   391.2  728.33     400  727.67   411.2  728.28   429.3  729.88   497.6  733.17
   546.3  734.87   585.4  735.34   604.9  736.48   653.6   742.1   682.9   748.1
   712.2  755.67   721.9  757.53   741.4  759.72     800  761.54   858.5  760.99
#Mann= 3 , 0 , 0
       0      .1       0   391.2    .045       0   411.2      .1       0
Bank Sta=391.2,411.2
XS Rating Curve= 0 ,0
Exp/Cntr=0.3,0.1

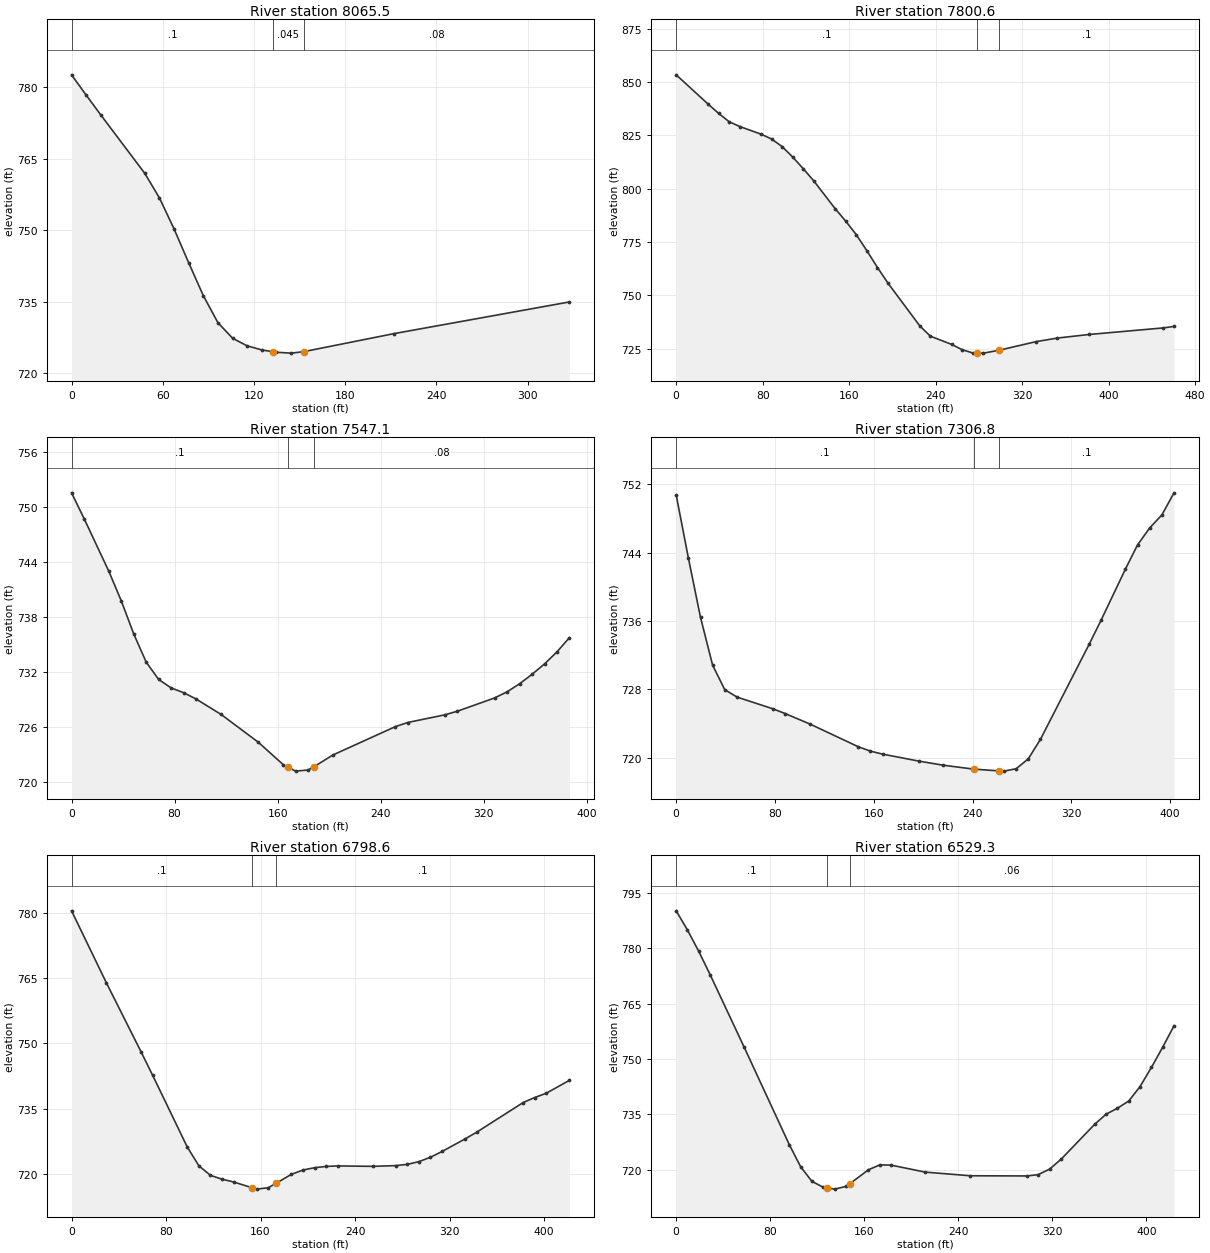
Type RM Length L Ch R = 1 ,8065.5  ,265,264.9,264.8
XS GIS Cut Line= 2
     1492210.079      307296.092     1492499.448      307449.402
#Sta/Elev= 18
       0  782.62     9.6  778.37    19.3  774.18    48.2  761.93    57.8   756.8
    67.4  750.31      77  743.22    86.7  736.27    96.3   730.6     106  727.33
   115.6  725.74   125.2  724.89   132.6  724.51   134.8   724.4   144.5  724.22
   152.6  724.52   211.9   728.3   327.5  734.96
#Mann= 3 , 0 , 0
       0      .1       0   132.6    .045       0   152.6     .08       0
Bank Sta=132.6,152.6
XS Rating Curve= 0 ,0
Exp/Cntr=0.3,0.1

Type RM Length L Ch R = 1 ,7800.6  ,260.4,253.5,246.5
XS GIS Cut Line= 2
     1491954.804      307462.092      1492362.79      307675.634
#Sta/Elev= 30
       0  853.47    29.4  839.79    39.2  835.42      49  831.46    58.8  829.21
    78.4  825.64    88.2  823.37      98   819.8   107.8  814.87   117.6  809.38
   127.4   803.6     147  790.69   156.8   784.8   166.6  778.44   176.4   770.9
   186.2  763.03     196  755.64   225.4   735.6   235.1  730.81   254.7  726.97
   264.5  724.46   274.3  722.93   278.4   722.9   284.1  722.85   298.4  724.16
   333.1  728.27   352.7  729.93   382.1  731.61   450.7  734.69   460.5  735.39
#Mann= 3 , 0 , 0
       0      .1       0   278.4    .045       0   298.4      .1       0
Bank Sta=278.4,298.4
XS Rating Curve= 0 ,0
Exp/Cntr=0.3,0.1

Type RM Length L Ch R = 1 ,7547.1  ,236.3,240.3,244.2
XS GIS Cut Line= 2
     1491969.881      307834.202     1492356.291        307842.2
#Sta/Elev= 29
       0  751.55     9.7  748.75      29  742.98    38.6  739.77    48.3  736.16
      58  733.08    67.6  731.21    77.3  730.28      87  729.76    96.6  729.08
     116   727.4   144.9  724.37   164.3  721.92     168  721.65   173.9  721.21
   183.6  721.33     188  721.67   202.9  722.97   251.2  726.05   260.9  726.51
   289.9  727.35   299.5  727.74   328.5  729.19   338.2  729.86   347.8  730.73
   357.5  731.76   367.2   732.9   376.8   734.2   386.5  735.76
#Mann= 3 , 0 , 0
       0      .1       0     168    .045       0     188     .08       0
Bank Sta=168,188
XS Rating Curve= 0 ,0
Exp/Cntr=0.3,0.1

Type RM Length L Ch R = 1 ,7306.8  ,508.2,508.2,507.7
XS GIS Cut Line= 2
     1491962.175      308038.191     1492365.112      308049.208
#Sta/Elev= 27
       0  750.76     9.8  743.44    19.7  736.43    29.5  730.84    39.3  727.98
    49.2  727.11    78.6  725.72    88.5  725.16   108.2  723.96   147.5  721.29
   157.3  720.78   167.1  720.43   196.6  719.61   216.3  719.13   241.2  718.67
   261.2  718.47   265.4  718.44   275.3  718.72   285.1  719.88   294.9  722.15
   334.3  733.26   344.1  736.12   363.8   742.1   373.6  744.92   383.4   746.9
   393.3  748.43   403.1  751.01
#Mann= 3 , 0 , 0
       0      .1       0   241.2    .045       0   261.2      .1       0
Bank Sta=241.2,261.2
XS Rating Curve= 0 ,0
Exp/Cntr=0.3,0.1

Type RM Length L Ch R = 1 ,6798.6  ,267.8,269.3,270.2
XS GIS Cut Line= 2
     1491853.732      308377.968     1492251.093       308518.56
#Sta/Elev= 30
       0  780.48    29.4  763.96    58.8  748.07    68.6  742.67      98  726.12
   107.8  721.82   117.6  719.62   127.4  718.73   137.2   718.1     153  716.75
   156.8  716.45   166.6  716.77     173  717.77   186.2  719.86     196  720.85
   205.8  721.38   215.6  721.67   225.4  721.79   254.9  721.69   274.5  721.86
   284.3  722.15   294.1  722.77   303.9  723.79   313.7  725.11   333.3  728.02
   343.1  729.56   382.3  736.36   392.1  737.52   401.9  738.51   421.5  741.48
#Mann= 3 , 0 , 0
       0      .1       0     153    .045       0     173      .1       0
Bank Sta=153,173
XS Rating Curve= 0 ,0
Exp/Cntr=0.3,0.1

Type RM Length L Ch R = 1 ,6529.3  ,211.7,213,216.4
XS GIS Cut Line= 2
      1491776.38      308610.065     1492159.627      308790.328
#Sta/Elev= 30
       0  790.13     9.6  784.94    19.2  779.15    28.9  772.82    57.8  753.21
    96.3  726.73   105.9  720.78   115.5  716.83   125.1  715.24   127.9  715.09
   134.8  714.73   144.4  715.46   147.9  716.24   163.6  719.98   173.3  721.31
   182.9  721.23   211.8  719.34   250.3  718.35   298.4   718.3     308  718.66
   317.6  720.15   327.3  722.78   356.2  732.36   365.8  735.04   375.4  736.66
     385   738.6   394.6  742.51   404.3  747.71   413.9   753.2   423.5  758.99
#Mann= 3 , 0 , 0
       0      .1       0   127.9    .045       0   147.9     .06       0
Bank Sta=127.9,147.9
XS Rating Curve= 0 ,0
Exp/Cntr=0.3,0.1

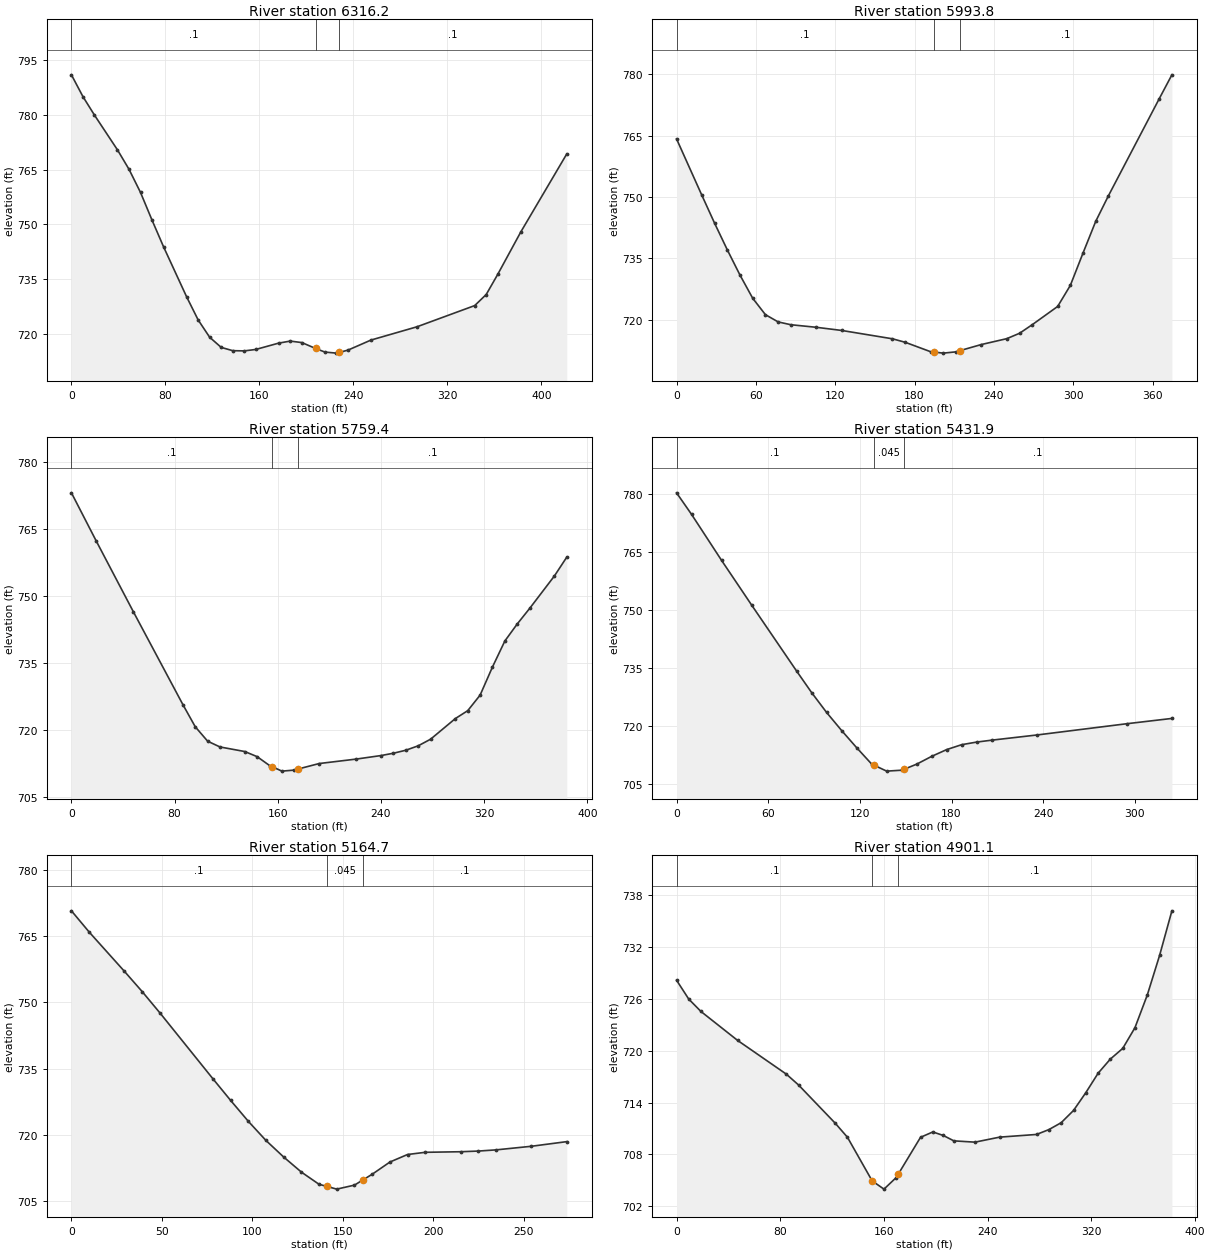
Type RM Length L Ch R = 1 ,6316.2  ,318.7,322.5,324.1
XS GIS Cut Line= 2
     1491674.597      308777.339       1492048.7      308971.999
#Sta/Elev= 30
       0  790.88     9.8  784.92    19.6  779.88    39.2  770.37      49  765.08
    58.8  758.75    68.6  751.19    78.5  743.84    98.1   730.2   107.9   723.9
   117.7  719.17   127.5  716.41   137.3  715.51   147.1  715.45   156.9  715.84
   176.5  717.58   186.3  718.13   196.2  717.72   207.8  716.12   215.8  715.13
   225.6  714.84   227.8  715.02   235.4  715.66     255  718.41   294.2  722.04
   343.3  727.83   353.1  730.85   362.9  736.35   382.5  747.92   421.7  769.27
#Mann= 3 , 0 , 0
       0      .1       0   207.8    .045       0   227.8      .1       0
Bank Sta=207.8,227.8
XS Rating Curve= 0 ,0
Exp/Cntr=0.3,0.1

Type RM Length L Ch R = 1 ,5993.8  ,234.3,234.3,234.2
XS GIS Cut Line= 2
     1491577.295      308938.379     1491839.576      309205.854
#Sta/Elev= 29
       0  764.19    19.2  750.37    28.8  743.57    38.4  737.07      48   730.9
    57.6  725.25    67.2  721.25    76.8  719.48    86.4  718.79   105.7  718.16
   124.9  717.39   163.3  715.35   172.9   714.5   192.1   712.2   194.4  712.12
   201.7  711.85   211.3  712.16   214.4  712.47   230.5  713.95   249.7  715.38
   259.4   716.7     269   718.8   288.2  723.25   297.8   728.4   307.4  736.31
     317  744.05   326.6  750.29     365  773.99   374.6  779.84
#Mann= 3 , 0 , 0
       0      .1       0   194.4    .045       0   214.4      .1       0
Bank Sta=194.4,214.4
XS Rating Curve= 0 ,0
Exp/Cntr=0.3,0.1

Type RM Length L Ch R = 1 ,5759.4  ,332.6,327.5,322.3
XS GIS Cut Line= 2
     1491403.897      309080.633     1491680.101      309347.579
#Sta/Elev= 30
       0  773.01    19.2  762.24      48  746.39    86.4   725.6      96  720.63
   105.6   717.4   115.2   716.1   134.4  715.08     144  713.93   153.6  711.95
   155.6  711.69   163.2  710.69   172.8  710.92   175.6  711.15   192.1  712.39
   220.9  713.39   240.1  714.18   249.7   714.7   259.3  715.37   268.9  716.36
   278.5  717.84   297.7  722.46   307.3  724.23   316.9  727.71   326.5  734.02
   336.1  739.84   345.7  743.65   355.3  747.12   374.5  754.39   384.1  758.61
#Mann= 3 , 0 , 0
       0      .1       0   155.6    .045       0   175.6      .1       0
Bank Sta=155.6,175.6
XS Rating Curve= 0 ,0
Exp/Cntr=0.3,0.1

Type RM Length L Ch R = 1 ,5431.9  ,270,267.3,264.4
XS GIS Cut Line= 2
     1491163.713      309321.363     1491455.527      309462.532
#Sta/Elev= 23
       0  780.37     9.8   774.8    29.5  762.85    49.1  751.32    78.6  734.19
    88.4  728.63    98.2  723.48   108.1  718.77   117.9  714.34   127.7  710.11
   129.1  709.85   137.5  708.28   147.4  708.52   149.1  708.79   157.2  710.09
     167  712.11   176.8  713.86   186.6  715.13   196.5  715.81   206.3   716.3
   235.8  717.64   294.7  720.56   324.2  721.93
#Mann= 3 , 0 , 0
       0      .1       0   129.1    .045       0   149.1      .1       0
Bank Sta=129.1,149.1
XS Rating Curve= 0 ,0
Exp/Cntr=0.3,0.1

Type RM Length L Ch R = 1 ,5164.7  ,265.8,263.6,261.3
XS GIS Cut Line= 2
     1491081.904      309602.122      1491346.33      309672.759
#Sta/Elev= 25
       0  770.78     9.8  765.97    29.3  757.05    39.1  752.46    48.9  747.63
    78.2  732.68      88  727.77    97.8  723.02   107.5   718.7   117.3  714.94
   127.1  711.52   136.8  708.77   141.2  708.28   146.6  707.67   156.4  708.58
   161.2  709.79   166.2  711.05     176  713.82   185.7  715.52   195.5  716.02
     215  716.15   224.8   716.3   234.6  716.57   254.2  717.39   273.7  718.44
#Mann= 3 , 0 , 0
       0      .1       0   141.2    .045       0   161.2      .1       0
Bank Sta=141.2,161.2
XS Rating Curve= 0 ,0
Exp/Cntr=0.3,0.1

Type RM Length L Ch R = 1 ,4901.1  ,403.2,402.4,389.7
XS GIS Cut Line= 4
      1490980.86      309868.537     1491177.262      309890.862
     1491194.161      309918.649     1491346.091      309916.455
#Sta/Elev= 30
       0  728.14     9.4  725.96    18.8  724.53    47.1  721.18    84.7  717.28
    94.1  716.03   122.4  711.61   131.8  709.99   150.9  704.94     160  703.99
   169.4  705.32   170.9  705.69   188.2  709.98   197.7   710.6   205.8  710.19
   213.9  709.57   230.2  709.42   249.2     710   277.7  710.31   287.2  710.87
   296.7  711.67   306.2  713.08   315.7  715.14   325.2  717.39   334.6  719.02
   344.2  720.26   353.6  722.65   363.1  726.42   372.6     731   382.1  736.16
#Mann= 3 , 0 , 0
       0      .1       0   150.9    .045       0   170.9      .1       0
Bank Sta=150.9,170.9
XS Rating Curve= 0 ,0
Exp/Cntr=0.3,0.1