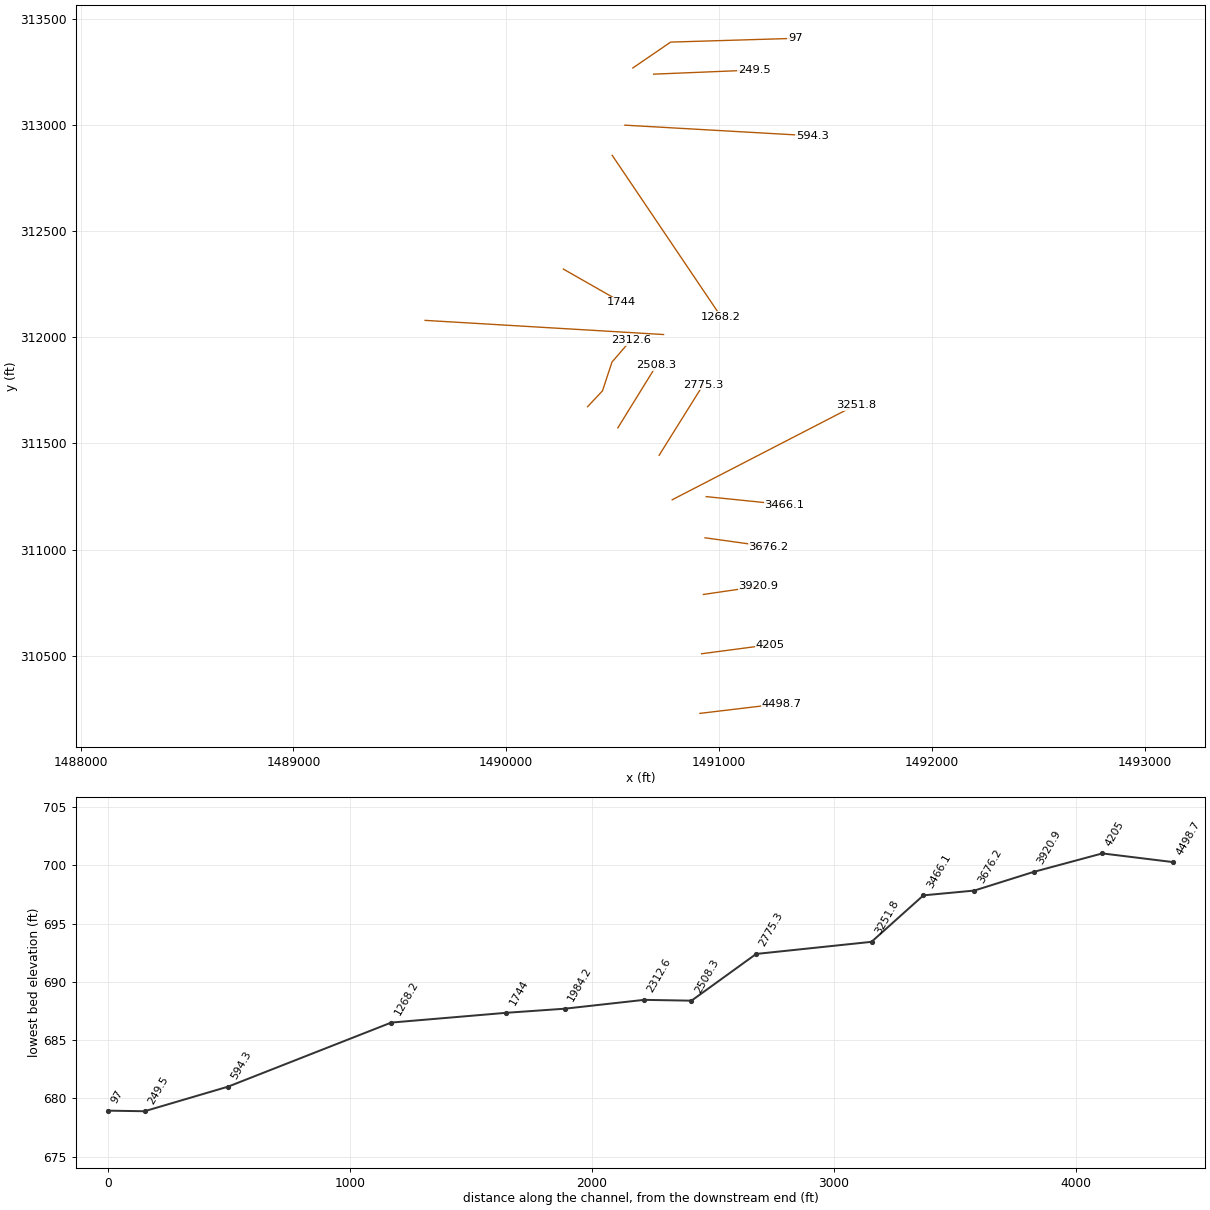
HEC-RAS study RFkFrencCr.prj: RFkFrencCr

--- RFkFrencCr.g01 (geometry) --- (continued)

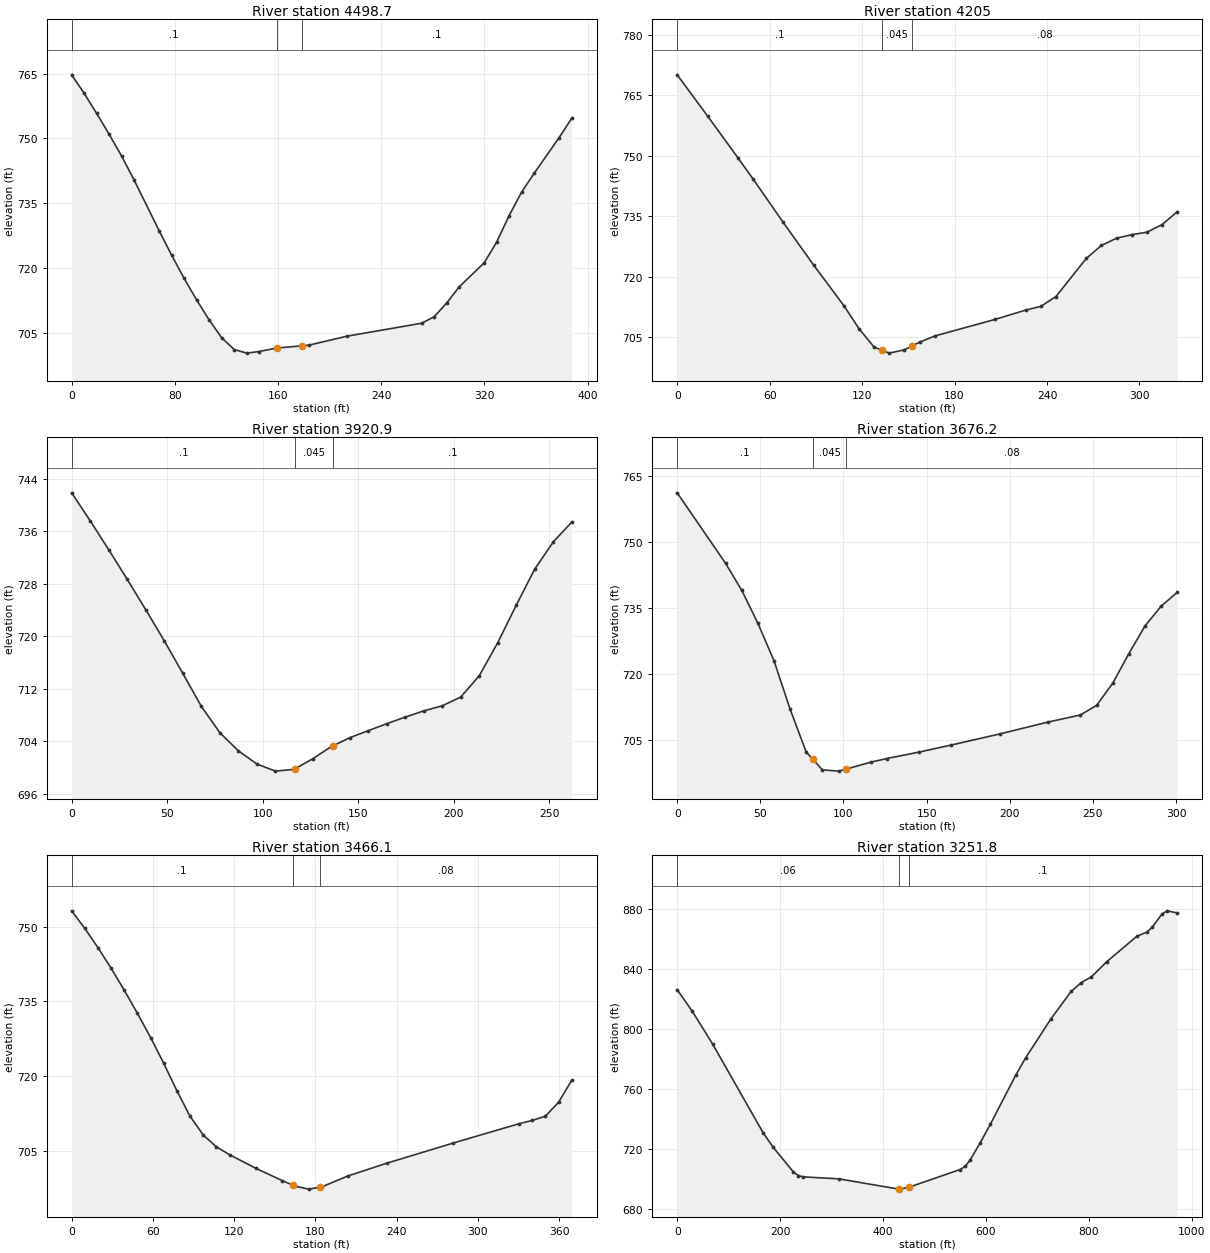
Type RM Length L Ch R = 1 ,4498.7  ,292.7,293.7,306.3
XS GIS Cut Line= 2
     1490910.231      310228.635     1491295.064      310274.746
#Sta/Elev= 30
       0   764.7     9.7  760.41    19.4  755.75    29.1  750.92    38.8  745.86
    48.4  740.34    67.8  728.63    77.5  722.94    87.2  717.57    96.9  712.59
   106.6  707.94   116.3  703.84     126  701.11   135.7  700.28   145.3  700.65
   158.8  701.45   178.8  701.98   184.1  702.14   213.2  704.19   271.3   707.2
     281   708.7   290.7  711.88   300.4  715.62   319.8  721.19   329.4  725.96
   339.1   732.1   348.8  737.56   358.5   741.9   377.9  750.19   387.6  754.62
#Mann= 3 , 0 , 0
       0      .1       0   158.8    .045       0   178.8      .1       0
Bank Sta=158.8,178.8
XS Rating Curve= 0 ,0
Exp/Cntr=0.3,0.1

Type RM Length L Ch R = 1 ,4205    ,283.8,284.1,284.2
XS GIS Cut Line= 2
      1490918.36      310509.463     1491240.012      310552.091
#Sta/Elev= 26
       0  770.07    19.7  759.85    39.3  749.54    49.2  744.24    68.8  733.46
    88.5   722.9   108.2  712.78     118  707.08   127.8  702.52   132.6  701.79
   137.6  701.03   147.5  701.86   152.6  702.84   157.3  703.74   167.2  705.29
   206.5  709.42   226.1   711.7     236  712.64   245.8  715.07   265.5  724.52
   275.3  727.74   285.1  729.53     295  730.42   304.8  731.02   314.6  732.89
   324.5  736.09
#Mann= 3 , 0 , 0
       0      .1       0   132.6    .045       0   152.6     .08       0
Bank Sta=132.6,152.6
XS Rating Curve= 0 ,0
Exp/Cntr=0.3,0.1

Type RM Length L Ch R = 1 ,3920.9  ,248.6,244.7,240.2
XS GIS Cut Line= 2
      1490926.44      310788.619     1491185.514       310826.65
#Sta/Elev= 30
       0  741.87     9.7  737.61    19.4   733.2    29.1  728.67    38.8  724.05
    48.5   719.3    58.2  714.34    67.9  709.31    77.6   705.3    87.3  702.53
      97  700.52   106.7  699.44   116.4  699.71   116.9  699.79   126.1   701.3
   135.8  703.16   136.9  703.31   145.5  704.52   155.2   705.6   164.9  706.66
   174.6  707.67   184.3  708.62     194   709.4   203.7  710.73   213.4  713.98
   223.1  719.03   232.8  724.75   242.4  730.22   252.2   734.4   261.8  737.39
#Mann= 3 , 0 , 0
       0      .1       0   116.9    .045       0   136.9      .1       0
Bank Sta=116.9,136.9
XS Rating Curve= 0 ,0
Exp/Cntr=0.3,0.1

Type RM Length L Ch R = 1 ,3676.2  ,209.3,210.1,210.6
XS GIS Cut Line= 2
     1490934.164      311055.445     1491231.941      311013.896
#Sta/Elev= 24
       0  761.08    29.1  745.06    38.8  738.93    48.5  731.46    58.2  722.92
    67.9  711.92    77.6  702.16    81.6   700.5    87.3  698.13      97  697.84
   101.6   698.3   116.4  699.88   126.1   700.7   145.5  702.17   164.9  703.78
     194  706.29   223.1     709   242.5   710.6   252.2  712.78   261.9   717.8
   271.6  724.53   281.3  730.82     291  735.31   300.7  738.47
#Mann= 3 , 0 , 0
       0      .1       0    81.6    .045       0   101.6     .08       0
Bank Sta=81.6,101.6
XS Rating Curve= 0 ,0
Exp/Cntr=0.3,0.1

Type RM Length L Ch R = 1 ,3466.1  ,202.7,214.4,229
XS GIS Cut Line= 2
     1490939.775      311249.295     1491307.084       311211.76
#Sta/Elev= 28
       0  753.14     9.7  749.62    19.4  745.78    29.2  741.61    38.9  737.21
    48.6   732.6    58.3  727.78      68   722.6    77.7  717.12    87.4  712.02
    97.2  708.25   106.9  705.89   116.6  704.31     136   701.6   155.5  699.13
   163.3  698.23   165.2  698.01   174.9  697.43   183.3  697.81   184.6  697.87
     204  700.07   233.2  702.66   281.8  706.66   330.4  710.53   340.1  711.18
   349.8  712.04   359.5   714.8   369.2  719.22
#Mann= 3 , 0 , 0
       0      .1       0   163.3    .045       0   183.3     .08       0
Bank Sta=163.3,183.3
XS Rating Curve= 0 ,0
Exp/Cntr=0.3,0.1

Type RM Length L Ch R = 1 ,3251.8  ,472.3,476.4,478.4
XS GIS Cut Line= 2
     1490779.921      311234.494     1491643.322      311681.043
#Sta/Elev= 30
       0  826.37    29.5  811.87    68.7  790.24   166.9  731.07   186.6  721.33
   225.8  704.89   235.6  702.42   245.5   701.6   314.2  700.29   430.4  693.48
     432  693.44   450.4  694.69   549.8  706.48   559.7  708.53   569.5  712.85
   589.1  724.38   608.8   736.7   657.8   769.2   677.5  781.03   726.6  806.96
   765.8   825.2   785.5  831.14   805.1  834.87   834.6   844.9   893.5  861.93
   913.1  864.79     923  867.83   942.6  876.88   952.4  878.92     972  877.51
#Mann= 3 , 0 , 0
       0     .06       0   430.4    .045       0   450.4      .1       0
Bank Sta=430.4,450.4
XS Rating Curve= 0 ,0
Exp/Cntr=0.3,0.1

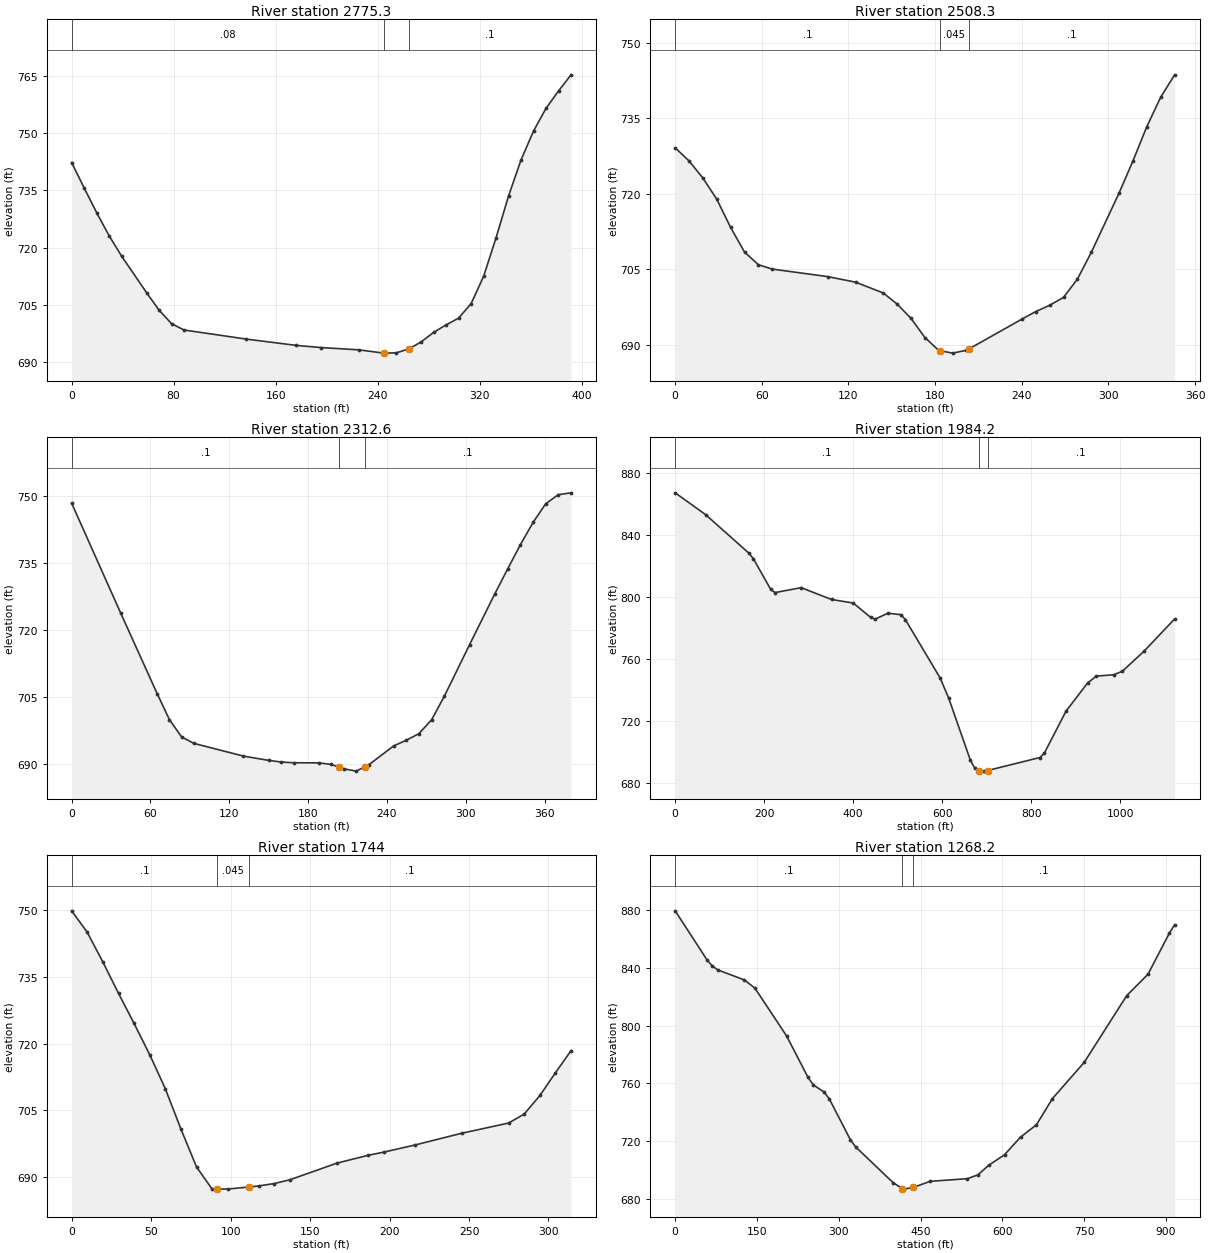
Type RM Length L Ch R = 1 ,2775.3  ,265.8,267,268
XS GIS Cut Line= 2
     1490718.604      311444.194     1490925.949      311776.613
#Sta/Elev= 30
       0  742.26     9.8  735.62    19.6  729.17    29.4   723.1    39.2  717.77
    58.8  708.21    68.6  703.64    78.4   700.1    88.2  698.45   137.1  696.07
   176.3  694.42   195.9  693.85   225.3  693.26   244.9   692.4     245   692.4
   254.7  692.47     265  693.57   274.2  695.33     284  697.83   293.8  699.79
   303.6  701.56   313.4  705.35   323.2  712.48     333  722.61   342.8  733.54
   352.6  742.98   362.4  750.52   372.2  756.46     382     761   391.8   765.2
#Mann= 3 , 0 , 0
       0     .08       0     245    .045       0     265      .1       0
Bank Sta=245,265
XS Rating Curve= 0 ,0
Exp/Cntr=0.3,0.1

Type RM Length L Ch R = 1 ,2508.3  ,191.9,195.7,198.7
XS GIS Cut Line= 2
     1490524.524      311573.213     1490706.014      311867.514
#Sta/Elev= 30
       0  729.12     9.6  726.52    19.2  723.12    28.8  718.93    38.4  713.32
      48  708.45    57.6  705.93    67.2  705.06   105.6  703.57   124.9  702.47
   144.1  700.32   153.7  698.12   163.3  695.28   172.9  691.49   182.5  688.92
   183.3  688.88   192.1  688.39   201.7  688.96   203.3   689.2   240.1  695.14
   249.7  696.64   259.3  697.88   268.9  699.45   278.5  703.07   288.1  708.36
   307.3  720.11     317  726.54   326.6  733.34   336.2  739.17   345.8   743.6
#Mann= 3 , 0 , 0
       0      .1       0   183.3    .045       0   203.3      .1       0
Bank Sta=183.3,203.3
XS Rating Curve= 0 ,0
Exp/Cntr=0.3,0.1

Type RM Length L Ch R = 1 ,2312.6  ,352.5,328.4,318.8
XS GIS Cut Line= 4
     1490382.396      311672.828     1490452.376      311747.424
     1490496.976      311883.018     1490585.173      311985.328
#Sta/Elev= 30
       0  748.42    37.2  723.91    65.1  705.79    74.4     700    83.7  696.11
      93  694.67   130.8  691.82   149.9  690.87   159.4   690.5   168.9  690.33
   187.9  690.31   197.4  689.97   203.4  689.36     207  688.99   216.5  688.46
   223.4  689.46     226  689.83     245  694.09   254.7  695.37   264.3  696.84
     274  699.96   283.6  705.19   302.9  716.78   322.2   728.2   331.9  733.73
   341.5   739.1   351.2  744.11   360.8  748.29   370.4  750.32   380.1  750.73
#Mann= 3 , 0 , 0
       0      .1       0   203.4    .045       0   223.4      .1       0
Bank Sta=203.4,223.4
XS Rating Curve= 0 ,0
Exp/Cntr=0.3,0.1

Type RM Length L Ch R = 1 ,1984.2  ,247.2,240.2,233.2
XS GIS Cut Line= 2
     1489618.954      312079.244      1490739.24      312012.576
#Sta/Elev= 30
       0  867.12    68.3  853.08   165.9  828.16   175.7  824.68   214.7  804.86
   224.4   802.8     283  805.99   351.3  798.36   400.1  796.08   439.2  786.83
   448.9  785.65   478.2   789.5   507.5  788.55   517.2  785.41   595.3  747.83
   614.8  734.65   663.6  694.56   673.4   689.6   682.1  687.94   692.9   687.7
   702.1   688.1   819.7  696.48   829.5  699.27   878.3  726.36   927.1  744.63
   946.6  748.98   985.6  749.82  1005.2  752.15    1054  765.12  1122.3  785.78
#Mann= 3 , 0 , 0
       0      .1       0   682.1    .045       0   702.1      .1       0
Bank Sta=682.1,702.1
XS Rating Curve= 0 ,0
Exp/Cntr=0.3,0.1

Type RM Length L Ch R = 1 ,1744    ,481.6,475.8,469.9
XS GIS Cut Line= 2
     1490268.697      312320.691     1490541.448      312164.736
#Sta/Elev= 26
       0  749.77     9.8  744.97    19.6  738.32    29.5  731.26    39.3   724.5
    49.1  717.52    58.9  709.89    68.7  700.88    78.6   692.3    88.4  687.35
    91.4  687.36    98.2  687.37   111.4  687.82   117.8  688.07   127.6  688.61
   137.5  689.47   166.9  693.18   186.6  694.94   196.4  695.65     216  697.25
   245.5  699.89   274.9  702.17   284.7  704.18   294.6  708.35   304.4  713.46
   314.2  718.41
#Mann= 3 , 0 , 0
       0      .1       0    91.4    .045       0   111.4      .1       0
Bank Sta=91.4,111.4
XS Rating Curve= 0 ,0
Exp/Cntr=0.3,0.1

Type RM Length L Ch R = 1 ,1268.2  ,660.8,673.9,686.9
XS GIS Cut Line= 2
     1490498.111       312856.22      1491009.35      312096.698
#Sta/Elev= 30
       0  879.56    58.4  845.51    68.2  841.29    77.9  838.62   126.6  831.65
   146.1     826   204.5  792.62   243.5  764.04   253.2  758.82   272.7  753.94
   282.5  749.19   321.4  720.62   331.2  715.68   399.3   691.1   416.2  686.92
   418.8  686.51   436.2  687.66   467.5  691.92   535.7  693.77   555.2  696.45
   574.7  703.02   603.9   710.4   633.1  722.57   662.3  731.13   691.5  749.24
     750  774.51   827.9  820.78   866.8  835.56   905.8  863.92   915.6  869.87
#Mann= 3 , 0 , 0
       0      .1       0   416.2    .045       0   436.2      .1       0
Bank Sta=416.2,436.2
XS Rating Curve= 0 ,0
Exp/Cntr=0.3,0.1

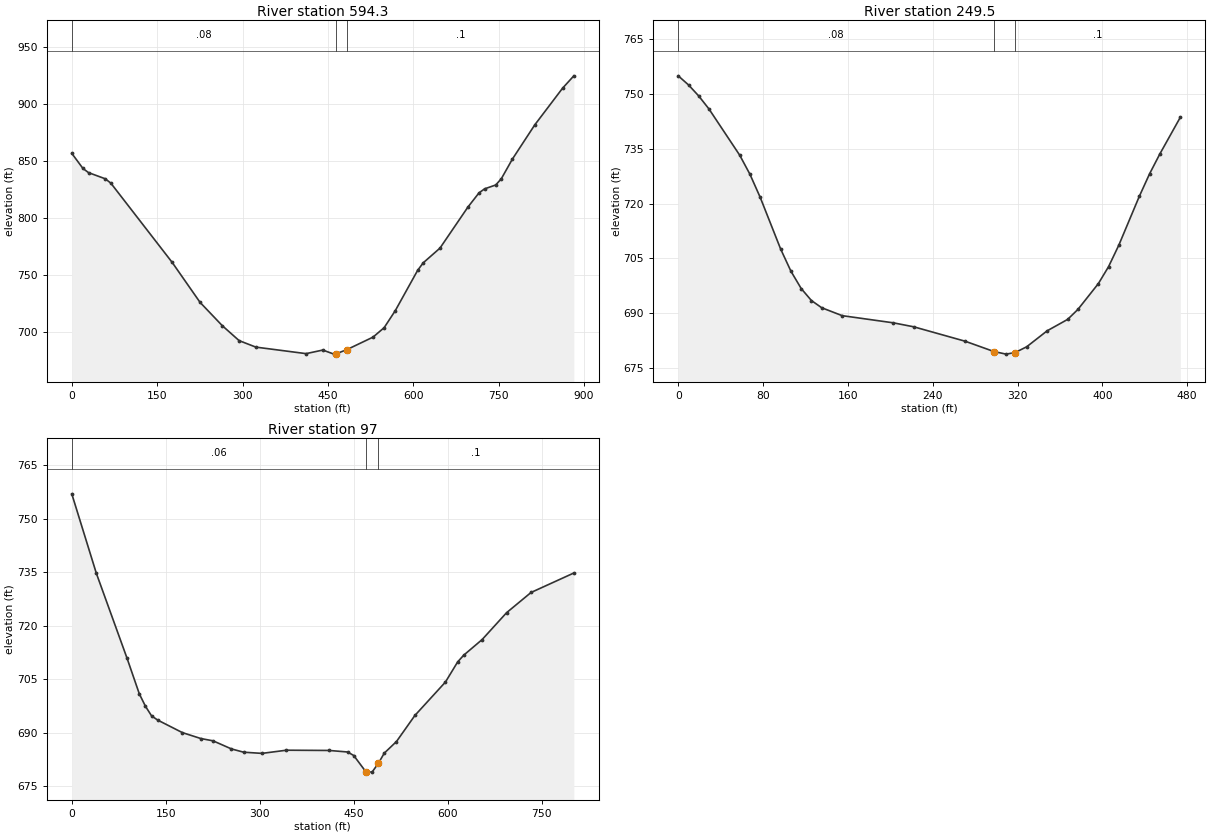
Type RM Length L Ch R = 1 ,594.3   ,340.4,344.9,347.6
XS GIS Cut Line= 2
     1490557.368      312998.454     1491437.891      312948.167
#Sta/Elev= 30
       0  856.88    19.6  843.66    29.4  839.99    58.8  834.59    68.6  830.79
   176.4  761.34   225.4  726.33   264.6  705.84     294  692.83   323.4  687.15
   411.6  681.44     441  684.58   460.6  681.01   463.6  681.12   483.6  685.03
   529.2   695.9   548.8   704.2   568.4  719.15   607.6  754.39   617.4  760.99
   646.8  773.85   695.8  809.73   715.4  822.26   725.2  825.77   744.8  829.17
   754.6  834.65   774.2  851.96   813.4  881.84   862.4  914.06     882  924.77
#Mann= 3 , 0 , 0
       0     .08       0   463.6    .045       0   483.6      .1       0
Bank Sta=463.6,483.6
XS Rating Curve= 0 ,0
Exp/Cntr=0.3,0.1

Type RM Length L Ch R = 1 ,249.5   ,156,152.4,150.4
XS GIS Cut Line= 2
     1490692.743      313238.622     1491165.833      313258.153
#Sta/Elev= 30
       0  754.85     9.7  752.37    19.3  749.36      29   745.8      58  733.18
    67.6     728    77.3  721.69    96.6  707.57   106.3  701.52     116  696.78
   125.6  693.53   135.3  691.56   154.6   689.4   202.9  687.44   222.2  686.35
   270.6  682.42   297.7  679.61   309.2   678.9   317.7  679.33   328.6   680.9
   347.9  685.26   367.2  688.37   376.9  691.09   396.2  698.14   405.8  702.75
   415.5  708.63   434.8  721.94   444.5   728.1   454.2  733.53   473.5  743.53
#Mann= 3 , 0 , 0
       0     .08       0   297.7    .045       0   317.7      .1       0
Bank Sta=297.7,317.7
XS Rating Curve= 0 ,0
Exp/Cntr=0.3,0.1

Type RM Length L Ch R = 1 ,97      ,91.6,97,102.4
XS GIS Cut Line= 3
      1490594.82      313267.706     1490772.733      313389.586
      1491357.72      313407.305
#Sta/Elev= 30
       0  757.03    39.2  734.73    88.2  710.89   107.8  700.89   117.6  697.41
   127.4  694.71   137.2  693.54   176.4  690.04   205.8  688.38   225.4  687.73
   254.7  685.46   274.2  684.54   303.4  684.21   342.5   685.1   410.7  685.03
     440   684.6   449.8  683.61   469.1  679.06     479  678.95   489.1  681.42
   498.5  684.28     518  687.54   547.3  694.84   596.1  704.23   615.6  709.88
   625.3  711.77   654.6  716.14   693.6  723.68   732.6  729.35   800.9  734.82
#Mann= 3 , 0 , 0
       0     .06       0   469.1    .045       0   489.1      .1       0
Bank Sta=469.1,489.1
XS Rating Curve= 0 ,0
Exp/Cntr=0.3,0.1

Chan Stop Cuts=-1
Use User Specified Reach Order=0
Composite Channel Slope=5